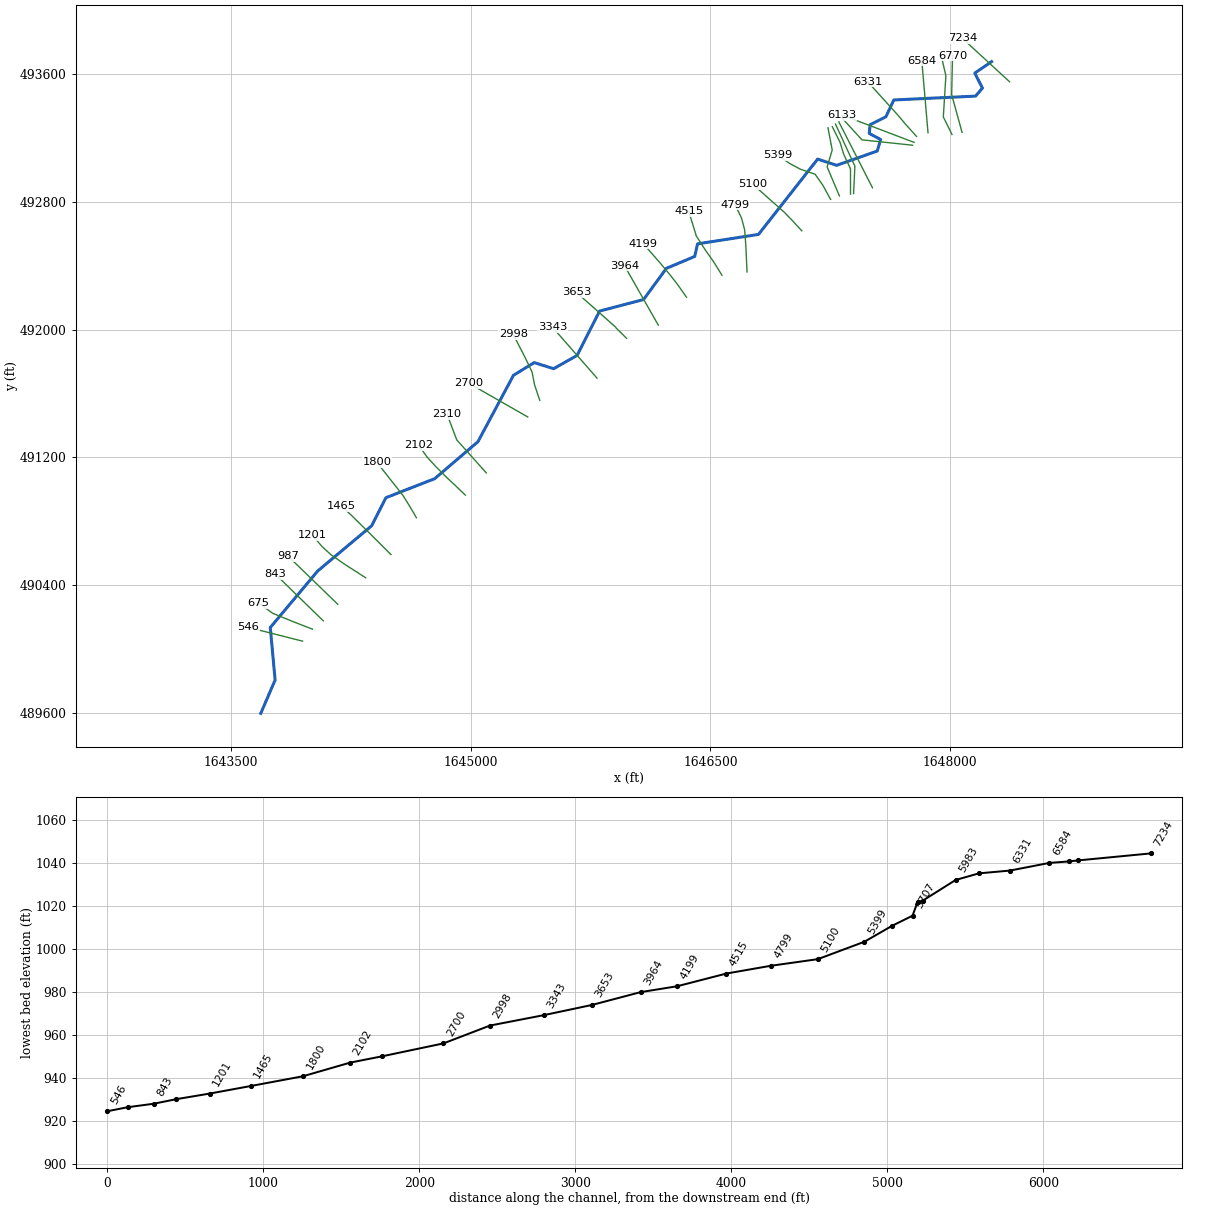
--- FrenchRn.prj (project) ---

Proj Title=FrenchRn
Current Plan=p01
Default Exp/Contr=0,0
English Units
Geom File=g01
Flow File=f01
Plan File=p01
BEGIN DESCRIPTION:
---------- MODELED AS PART OF WVEM CTP PROGRAM, 2025----------
Stream Name: French Run
Flood Zone: AFH
Marshall County, WV
HEC-RAS Version: RAS 6.6
Vertical Datum: NAVD88
Projection: NAD 1983 StatePlane West Virginia N FIPS 4701 (US Feet)
Terrain: 1-meter West Virginia FEMA R3 South Central (collected 2018-2019)
Land Use: 2024 NLCD
Hydrologic Method:
Duda et al., "Estimation of magnitude and frequency of floods for rural, unregulated streams in and near Virginia and West Virginia." September 8, 2025.
Additional Model Notes:
None
END DESCRIPTION:
DSS Export Rating Curves= 0
DSS Export Rating Curve Sorted= 0
DSS Export Volume Flow Curves= 0
DXF OffsetX= 0
DXF OffsetY= 0
DXF ScaleX= 0
DXF ScaleY= 0

--- FrenchRn.p01 (plan) ---

Plan Title=Floodplain
Program Version=6.60
Short Identifier=Floodplain
Geom File=g01
Flow File=f01
Subcritical Flow
K Sum by GR= 0
Std Step Tol= 0.01
Critical Tol= 0.01
Num of Std Step Trials= 20
Max Error Tol= 0.3
Flow Tol Ratio= 0.001
Split Flow NTrial= 30
Split Flow Tol= 0.02
Split Flow Ratio= 0.02
Log Output Level= 0
Friction Slope Method= 1
Unsteady Friction Slope Method= 2
Unsteady Bridges Friction Slope Method= 1
Parabolic Critical Depth
Global Vel Dist= 0 , 0 , 0
Global Log Level= 0
CheckData=False
Encroach Param=-1 ,0,0, 0
Flow Ratio Tolerance=0.1
Flow Ratio Min Ratio=0.5
Flow Ratio Max Ratio=4
Flow Ratio Max Iterations= 10
Mapping Interval=1HOUR
Computation Time Step Use Courant=        0
Computation Time Step Use Time Series=    0
Computation Time Step Count To Double=0
Computation Time Step Max Doubling=0
Computation Time Step Max Halving=0
Computation Time Step Residence Courant=0
Run HTab= 0
Run UNet= 0
Run Sediment= 0
Run PostProcess= 0
Run WQNet= 0
Run RASMapper=-1
UNET Theta= 0
UNET Theta Warmup= 0
UNET ZTol= 0
UNET ZSATol= 0
UNET MxIter= 0
UNET Max Iter WO Improvement= 0
UNET MaxInSteps= 0
UNET DtIC= 0
UNET DtMin= 0
UNET MaxCRTS= 0
UNET WFStab= 0
UNET SFStab= 0
UNET WFX= 1
UNET SFX= 1
UNET Gravity=32.17405
UNET 1D Methodology=Finite Difference
UNET DSS MLevel= 1
UNET Pardiso=0
UNET DZMax Abort= 0
UNET Use Existing IB Tables= 0
UNET Froude Reduction=False
UNET Froude Limit= 0
UNET Froude Power= 0
UNET D1 Cores= 0
UNET WindReference=Eulerian
UNET WindDragFormulation=Hsu (1988)
UNET D2 Coriolis=0
UNET D2 Cores= 0
UNET D2 Theta= 1
UNET D2 Theta Warmup= 1
UNET D2 Z Tol= 0.01
UNET D2 Volume Tol= 0.01
UNET D2 Max Iterations= 20
UNET D2 Advanced Convergence=0
UNET D2 WS Max Tol=0.15
UNET D2 WS RMS Tol=0.002
UNET D2 WS Stall Tol=1
UNET D2 Equation= 0
UNET D2 RampUpFraction=0.1
UNET D2 TimeSlices= 1
UNET D2 Turbulence Formulation=Non-Conservative (original)
UNET D2 Eddy Viscosity=0.3
UNET D2 Transverse Eddy Viscosity=0.1
UNET D2 Smagorinsky Mixing=0
UNET D2 BCVolumeCheck=0
UNET D2 Cores=0
UNET D2 SolverType=PARDISO (Direct)
UNET D2 Minimum Iterations= 3
UNET D2 Maximum Iterations= 30
UNET D2 Restart Number= 10
UNET D2 Relaxation Coeff=1.3
UNET D2 SOR Precondition Iterations= 10
UNET D2 ILUT Maximum Fill= 8
UNET D2 ILUT Tolerance=1E-08
UNET D2 Convergence Tolerance=0.00001
PS Theta= 1
PS WS Tol= 0.01
PS Volume Tol= 0.01
PS Max Iterations= 20
PS Equation= 0
PS Advance Time Step=-1
PS Target Courant=0.9
PS Time Slices= 1
PS Iterate With 2D=0
PS Project Initial WSE from DS=-1
PS Ramp Up Initial WSE from US=-1
PS Cores=0
UNET D1D2 MaxIter= 0
UNET D1D2 ZTol=0.01
UNET D1D2 QTol=0.1
UNET D1D2 MinQTol=1
Write IC File= 0
Write IC File at Fixed DateTime=0
Write IC File at Sim End=0
Echo Input=False
Echo Parameters=False
Echo Output=False
Write Detailed= 0
HDF Write Warmup=0
HDF Write Time Slices=0
HDF Flush=0
HDF Compression= 1
HDF Chunk Size= 1
HDF Spatial Parts= 1
HDF Use Max Rows=0
HDF Fixed Rows= 1
Calibration Method= 0
Calibration Iterations= 20
Calibration Max Change=0.05
Calibration Tolerance=0.2
Calibration Maximum=1.5
Calibration Minimum=0.5
Calibration Optimization Method= 1
WQ AD Non Conservative
WQ ULTIMATE=-1
WQ Max Comp Step=1HOUR
WQ Output Interval=15MIN
WQ Output Selected Increments= 0
WQ Create Restart=0
WQ Fixed Restart=0
WQ System Summary=0
WQ Write To DSS=0
Sorting and Armoring Iterations= 10
XS Update Threshold= 0.02
Bed Roughness Predictor= 0
Processes Affected by Predictor=Sediment Only
Hydraulics Update Threshold= 0.02
Energy Slope Method= 1
Volume Change Method= 1
Sediment Retention Method= 0
Sediment TS Multiplier= 1
Warm Up Method= 0
XS Weighting Method= 0
Number of US Weighted Cross Sections= 1
Number of DS Weighted Cross Sections= 1
Upstream XS Weight=0
Main XS Weight=1
Downstream XS Weight=0
Number of DS XS's Weighted with US Boundary= 1
Upstream Boundary Weight= 1
Weight of XSs Associated with US Boundary= 0
Number of US XS's Weighted with DS Boundary= 1
Downstream Boundary Weight= 0.5
Weight of XSs Associated with DS Boundary= 0.5
Percentile Method= 0
Sediment Output Level= 3
Mass or Volume Output= 0
Output Increment Type= 1
Profile and TS Output Increment= 1
Transport Output Increment 1
XS Output Flag= 0
XS Output Increment= 10
Read HDF5 Sediment Hotstart= 0
Sediment Hotstart Type= 0
Write Gradation File= 0
Read Gradation Hotstart= 0
Write HDF5 File= 1
Write Binary Output= 1
Write DSS Sediment File= 0
DSS Sediment Output Type= 1
SV Curve= 0
Specific Gage Flag= 0
Subcell Erosion Methods= 0
Subcell Deposition Methods= 0
Advection Scheme= 1
Matrix Solver= 0
Implicit Weighting Factor= 1
Maximum Outer Loop Convergence Iterations= 5
Convergence Maximum Absolute= 0.001
Convergence RMSE= 0.0001
Grain Fractions Max Abs Error= 0.001
Max Subgrid Regions= 1
Max Subgrid Length Scale= 3.402823E+38
Initial Layer Thickness= 3
Min Layer Thickness= 0.1
Max Layer Thickness= 6
Number of Layers= 5

--- FrenchRn.f01 (steady flow) ---

Flow Title=Flow
Program Version=6.60
Number of Profiles= 1
Profile Names=P100yr
River Rch & RM=FrenchRn,Main,7234
     798
River Rch & RM=FrenchRn,Main,4199
     888
Boundary for River Rch & Prof#=FrenchRn,Main            , 1
Up Type= 0
Dn Type= 3
Dn Slope=0.009789
DSS Import GetInterval= 0
DSS Import GetPeak= 0
DSS Import FillOption= 0

--- FrenchRn.g01 (geometry) ---

Geom Title=Geometry
Program Version=6.60

River Reach=FrenchRn        ,Main
Reach XY= 30
     1648259.717      493676.664     1648154.529      493604.927
     1648202.319      493510.935     1648159.204      493460.914
     1647647.698      493436.826     1647598.292      493331.363
     1647499.739      493282.277     1647493.876      493227.523
     1647565.377      493189.219     1647543.939      493117.104
        1647290.      493027.839     1647170.982        493066.7
     1646800.818      492595.357     1646419.252      492536.368
     1646401.806      492457.348     1646224.397      492382.925
     1646081.688      492187.835     1645806.595      492115.615
     1645665.168        491837.7     1645518.622      491755.026
     1645397.336       491793.12     1645267.487       491713.77
     1645044.878      491297.798     1644774.211      491066.606
      1644469.08      490947.564      1644380.14      490772.147
     1644042.717      490489.456     1643745.383      490135.062
     1643775.705      489806.501     1643685.765      489597.775

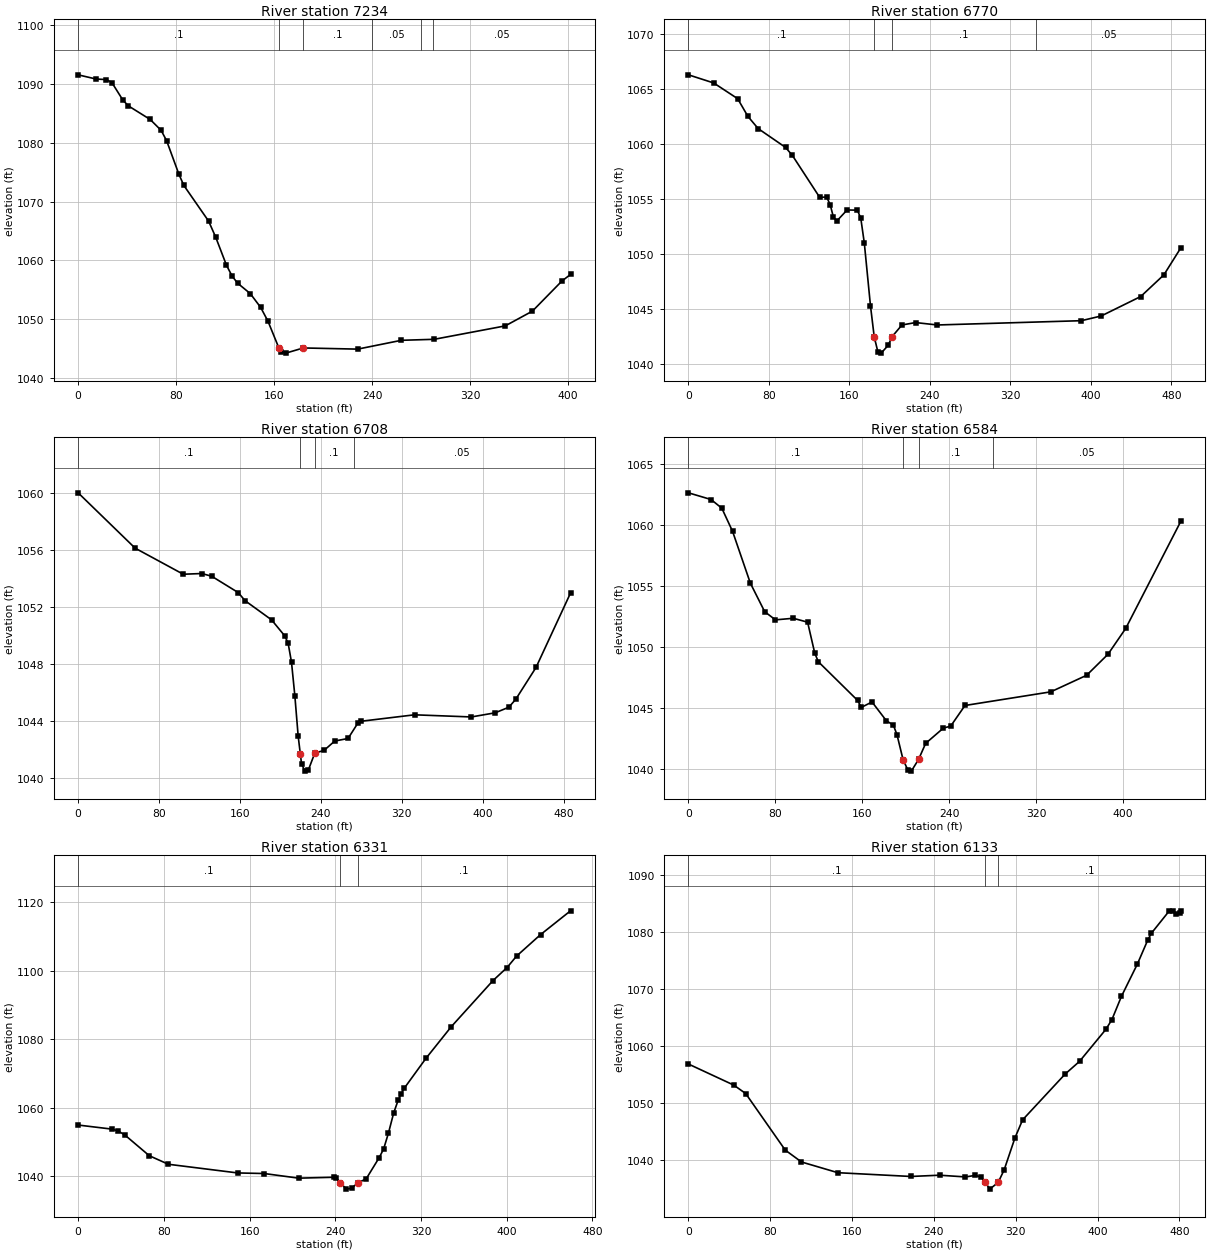
Type RM Length L Ch R = 1 ,7234    ,463.4,463.8,442.7
XS GIS Cut Line= 2
1648372.57925804 493550.297152141648076.80610108493822.521972086
#Sta/Elev= 30
       0 1091.56    14.5 1090.85    23.1 1090.75    27.6 1090.22    36.5 1087.27
      41 1086.28    58.8 1083.97    67.7 1082.13    72.2 1080.37    82.3 1074.63
    86.3 1072.75   106.5 1066.69   112.3 1063.96   121.1 1059.18   125.7 1057.34
   130.2 1056.13   140.5 1054.37     149 1052.02     155 1049.66  163.94 1045.09
   165.8 1044.48   169.5 1044.24   183.9 1045.12   228.2 1044.92   263.9 1046.42
   290.7 1046.59   348.7 1048.87   370.9 1051.38   395.1 1056.52     402 1057.61
#Mann= 6 ,-1,0
       0      .1       0  163.94    .045       0   183.9      .1       0
     240     .05       0     280      .1       0     290     .05       0
Bank Sta=163.94,183.9
XS Rating Curve= 0 ,0
Exp/Cntr(USF)=0,0
Exp/Cntr=0.3,0.1

Type RM Length L Ch R = 1 ,6770    ,64.7,62.5,58.5
XS GIS Cut Line= 3
1648074.74207203493234.110100721 1648009.7906335493470.943685662
1648015.14891334493714.674869417
#Sta/Elev= 30
       0 1066.31    25.1 1065.57    48.9 1064.14    59.1 1062.53    69.3 1061.42
    96.5 1059.71   103.3 1058.98   130.5 1055.16   137.3  1055.2   140.9  1054.5
   144.1 1053.36   147.5 1053.02   157.7 1054.02   167.9    1054   171.3 1053.27
   174.8 1051.02   180.9 1045.33  184.641042.493   188.4 1041.07   191.6    1041
   198.6 1041.72  202.371042.492   212.2 1043.56   225.8 1043.78   247.4 1043.56
   390.6 1043.95   410.3 1044.38   449.6 1046.15   472.6 1048.12   489.4 1050.57
#Mann= 4 ,-1,0
       0      .1       0  184.64    .045       0  202.37      .1       0
  345.58     .05       0
Bank Sta=184.64,202.37
XS Rating Curve= 0 ,0
Exp/Cntr(USF)=0,0
Exp/Cntr=0.3,0.1

Type RM Length L Ch R = 1 ,6708    ,121.8,123.9,125.3
XS GIS Cut Line= 4
1648011.78229349493220.9375049821647957.65513797493330.497044645
1647973.61498354493587.9825531761647949.72796981493691.778357924
#Sta/Elev= 30
       0 1060.03    56.3 1056.15   103.9 1054.32   122.2 1054.37     132 1054.18
   158.3 1053.03   164.9 1052.47   191.2 1051.12   204.3 1049.99   207.6 1049.47
   210.9 1048.15   214.2  1045.8   217.5 1042.96  219.581041.742   220.8 1041.03
   224.1 1040.51   227.4 1040.56   233.9 1041.77   243.2 1041.97   253.6 1042.62
   266.8  1042.8   276.7  1043.9   279.9 1044.01   332.5 1044.46   388.7 1044.31
   412.2  1044.6   425.7 1044.99   432.6 1045.55   452.6 1047.78   486.7    1053
#Mann= 4 ,-1,0
       0      .1       0  219.58    .045       0   233.9      .1       0
   272.2     .05       0
Bank Sta=219.58,233.9
XS Rating Curve= 0 ,0
Exp/Cntr(USF)=0,0
Exp/Cntr=0.3,0.1

Type RM Length L Ch R = 1 ,6584    ,245,253.1,254
XS GIS Cut Line= 2
1647861.84073417 493230.998113091647822.82777833493682.602632186
#Sta/Elev= 30
       0 1062.67    20.8 1062.12    30.7 1061.41    40.6 1059.51      57 1055.25
    70.2 1052.91    80.1 1052.24    96.5 1052.37   109.7 1052.05   116.3  1049.5
   119.6  1048.8   155.8 1045.62   159.1 1045.05     169  1045.5   182.2 1043.96
   188.7 1043.59     192 1042.81  197.551040.774   201.9 1039.93   205.2 1039.82
  211.821040.775   218.4  1042.1   234.8 1043.36   241.4 1043.51   254.6 1045.21
   333.6 1046.33   366.6 1047.69   386.3 1049.42   402.6 1051.54   453.3 1060.33
#Mann= 4 ,-1,0
       0      .1       0  197.55    .045       0  211.82      .1       0
     280     .05       0
Bank Sta=197.55,211.82
XS Rating Curve= 0 ,0
Exp/Cntr(USF)=0,0
Exp/Cntr=0.3,0.1

Type RM Length L Ch R = 1 ,6331    ,193.6,198.1,199.2
XS GIS Cut Line= 4
1647789.74234617493208.7566623391647714.97313876493291.954330593
1647683.17861544493330.7363727291647483.79402618 493551.53211051
#Sta/Elev= 30
       0 1054.94    31.3 1053.76      37 1053.24    43.3 1052.11    66.4 1045.99
    84.2  1043.5   148.9 1040.97   173.6  1040.8   205.8 1039.45   238.6 1039.71
   240.9 1039.52  244.651038.092   250.4 1036.25   255.3 1036.53  261.051038.093
   268.8 1039.24     281 1045.46   285.1 1047.97   289.6  1052.6   294.5  1058.5
   298.7 1062.22   301.3    1064   304.2 1065.61   324.5 1074.35   348.3 1083.65
   387.1 1097.05   400.3 1100.88   409.2 1104.22   431.5 1110.46   459.5 1117.41
#Mann= 3 ,-1,0
       0      .1       0  244.65    .045       0  261.05      .1       0
Bank Sta=244.65,261.05
XS Rating Curve= 0 ,0
Exp/Cntr(USF)=0,0
Exp/Cntr=0.3,0.1

Type RM Length L Ch R = 1 ,6133    ,151,149.9,150.9
XS GIS Cut Line= 2
1647774.71973842493171.3695980011647324.62106016493342.260800498
#Sta/Elev= 30
       0  1056.9    44.4  1053.2      56 1051.72    94.6 1041.82   110.5 1039.73
   146.1 1037.85   217.4 1037.19   245.5 1037.41   270.8 1037.11   280.6 1037.38
     286 1037.09  290.381036.139   294.6 1034.97  302.831036.141   308.7 1038.36
   319.2 1043.93   326.7 1047.11   368.3 1055.14   382.4 1057.37   408.1 1062.97
     414 1064.67   423.4 1068.78     439 1074.45     449  1078.6   452.6 1079.82
   470.1 1083.74   473.6 1083.75   477.1 1083.28   480.6 1083.44   481.4 1083.76
#Mann= 3 ,-1,0
       0      .1       0  290.38    .045       0  302.83      .1       0
Bank Sta=290.38,302.83
XS Rating Curve= 0 ,0
Exp/Cntr(USF)=0,0
Exp/Cntr=0.3,0.1

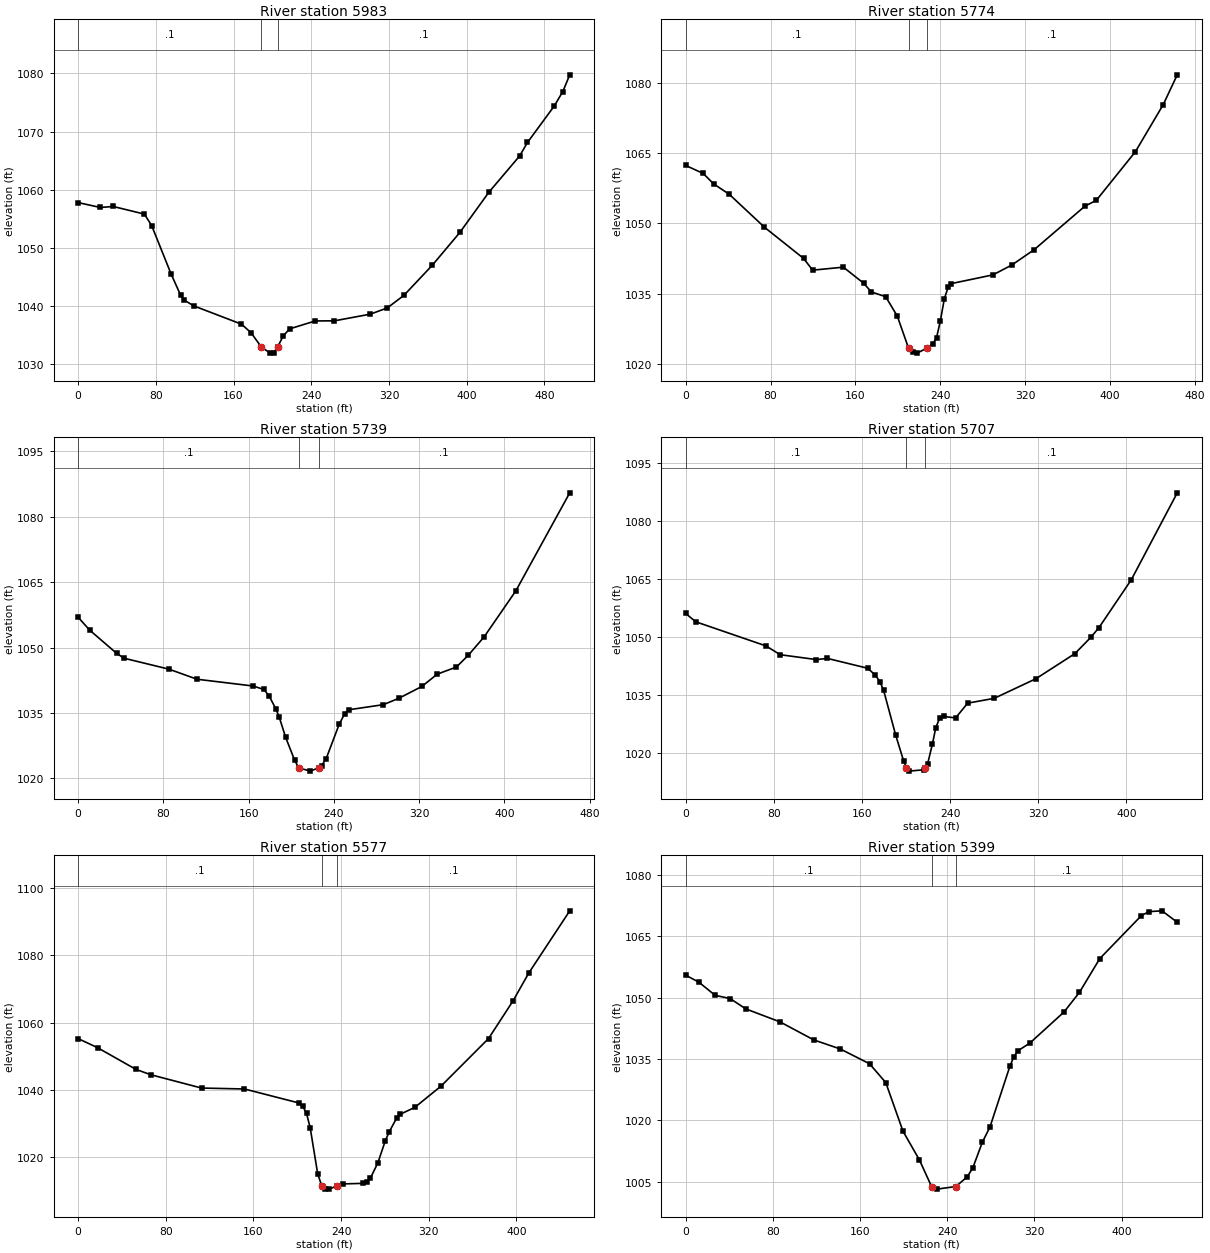
Type RM Length L Ch R = 1 ,5983    ,217.8,208.7,201.1
XS GIS Cut Line= 3
1647764.86258977493153.5393663821647448.49136036493187.273474418
1647321.76052207493325.856837158
#Sta/Elev= 30
       0 1057.78    22.9 1056.94    36.1 1057.11    68.2  1055.8    75.7 1053.82
    95.5 1045.57   105.4 1041.87   108.7 1041.05   118.9 1040.01   168.1 1036.86
     178 1035.38  188.651032.903   197.8 1031.87   201.1 1031.94   205.4 1032.94
     211  1034.8   217.6 1036.04   244.1 1037.41   263.8 1037.43   300.8 1038.58
   318.2 1039.65   335.3 1041.81   364.5 1046.99   392.9 1052.64   422.8 1059.57
   454.4  1065.8   462.5 1068.13     490 1074.39   498.9  1076.9     506 1079.77
#Mann= 3 ,-1,0
       0      .1       0  188.65    .045       0   205.4      .1       0
Bank Sta=188.65,205.4
XS Rating Curve= 0 ,0
Exp/Cntr(USF)=0,0
Exp/Cntr=0.3,0.1

Type RM Length L Ch R = 1 ,5774    ,35.3,34.8,34.5
XS GIS Cut Line= 2
1647514.27076397492886.974775245 1647303.8372446493299.566338503
#Sta/Elev= 30
       0 1062.34    16.5 1060.64    26.4 1058.41    41.2 1056.17    74.3 1049.16
   111.1 1042.53   119.7 1040.02   148.6 1040.66   167.7 1037.24     175 1035.38
   188.5 1034.36   199.4 1030.24  210.081023.366     214 1022.51   217.9 1022.34
  227.151023.366   232.7 1024.27   236.4 1025.62     240 1029.21   243.7 1033.87
   247.4 1036.45   249.7 1037.13   289.6 1039.02   307.4 1041.13   328.4 1044.39
   376.3 1053.68   386.9 1054.89   423.8 1065.28     450 1075.31   463.2 1081.65
#Mann= 3 ,-1,0
       0      .1       0  210.08    .045       0  227.15      .1       0
Bank Sta=210.08,227.15
XS Rating Curve= 0 ,0
Exp/Cntr(USF)=0,0
Exp/Cntr=0.3,0.1

Type RM Length L Ch R = 1 ,5739    ,32.2,32.4,32.2
XS GIS Cut Line= 3
1647396.08304154492851.5304540131647404.17681122493022.481679863
1647282.52767631493285.877651203
#Sta/Elev= 30
       0 1056.96    10.8    1054    36.3 1048.63    43.2 1047.54    85.3 1045.03
   111.6 1042.72   164.2 1041.17   174.3 1040.37   179.1 1038.93   185.7 1035.84
   188.8 1033.95   194.7  1029.4   203.2 1024.11  206.941022.397   217.8 1021.63
  225.751022.396   228.5 1022.91   232.7 1024.47     245 1032.41   250.2 1034.85
   253.8 1035.71   286.3 1036.88   300.8 1038.33   322.5 1041.06   336.9 1043.88
     355 1045.53   366.2 1048.25     381 1052.46   410.7    1063   461.3 1085.51
#Mann= 3 ,-1,0
       0      .1       0  206.94    .045       0  225.75      .1       0
Bank Sta=206.94,225.75
XS Rating Curve= 0 ,0
Exp/Cntr(USF)=0,0
Exp/Cntr=0.3,0.1

Type RM Length L Ch R = 1 ,5707    ,134.2,130.6,123.7
XS GIS Cut Line= 5
1647376.64731271 492847.570378271647376.75959179493006.081183765
1647334.17437512493097.0708311831647311.57205813493170.916155923
1647262.77589588493269.430394593
#Sta/Elev= 30
       0 1056.07     9.2 1053.91    72.8 1047.68    85.9 1045.39   118.7 1044.13
   128.6 1044.44   165.3 1041.88   172.2 1040.08   176.2 1038.45   179.6 1036.22
   190.6 1024.59   197.9 1017.82  200.361016.161   202.3 1015.27     216 1015.61
  217.491016.161   219.6 1017.18     224 1022.36   226.9 1026.43   230.5 1029.01
   234.1 1029.41     245 1029.04   255.9 1032.86     280  1034.1   317.8 1039.17
   353.2 1045.67   367.8 1049.93   375.1 1052.42   404.4 1064.79   446.1 1087.28
#Mann= 3 ,-1,0
       0      .1       0  200.36    .045       0  217.49      .1       0
Bank Sta=200.36,217.49
XS Rating Curve= 0 ,0
Exp/Cntr(USF)=0,0
Exp/Cntr=0.3,0.1

Type RM Length L Ch R = 1 ,5577    ,165,178,192.6
XS GIS Cut Line= 4
1647307.22074938492836.326041133 1647230.4315484493017.827788894
1647262.23313669493123.3159841751647235.86108787493262.157064728
#Sta/Elev= 30
       0 1055.25    17.7 1052.56    52.8 1046.11    66.3 1044.53   112.6 1040.58
   151.8  1040.3   201.5 1036.15   204.9 1035.23   208.4 1033.06   211.8 1028.73
   218.6 1015.14  222.311011.567   225.5 1010.67   228.9 1010.59   236.41011.567
   241.9 1012.14   259.8  1012.3   263.2 1012.65   266.6 1013.78   273.5 1018.38
   280.3 1024.94   283.7 1027.49   290.6 1031.64     294 1032.81   307.3 1034.86
   331.1 1041.14   374.5 1055.27   396.8 1066.42   411.2  1074.7   448.6 1093.16
#Mann= 3 ,-1,0
       0      .1       0  222.31    .045       0   236.4      .1       0
Bank Sta=222.31,236.4
XS Rating Curve= 0 ,0
Exp/Cntr(USF)=0,0
Exp/Cntr=0.3,0.1

Type RM Length L Ch R = 1 ,5399    ,300.7,298.6,291.6
XS GIS Cut Line= 6
1647251.98882851492814.6354033351647204.83439526492901.131949499
1647155.39256501492971.9044457531647060.69131084493004.528724343
1646993.62189117493040.9256331771646920.22866526493092.540687427
#Sta/Elev= 30
       0 1055.52    12.1 1053.81      27 1050.59    40.8 1049.79    55.3 1047.25
    86.6 1044.08   117.6 1039.67     142 1037.44   168.7 1033.84   183.6 1029.23
   199.4 1017.33   214.5 1010.29  225.591003.802   230.6 1003.16   247.91003.801
   258.4 1006.19   263.5  1008.4   272.2 1014.64   279.2 1018.38   297.4 1033.18
   301.1 1035.56   304.9 1037.03   315.7 1038.88   347.1  1046.5   361.3 1051.32
   379.9 1059.56   418.1 1070.09     425 1071.06     437 1071.26     451 1068.46
#Mann= 3 ,-1,0
       0      .1       0  225.59    .045       0   247.9      .1       0
Bank Sta=225.59,247.9
XS Rating Curve= 0 ,0
Exp/Cntr(USF)=0,0
Exp/Cntr=0.3,0.1

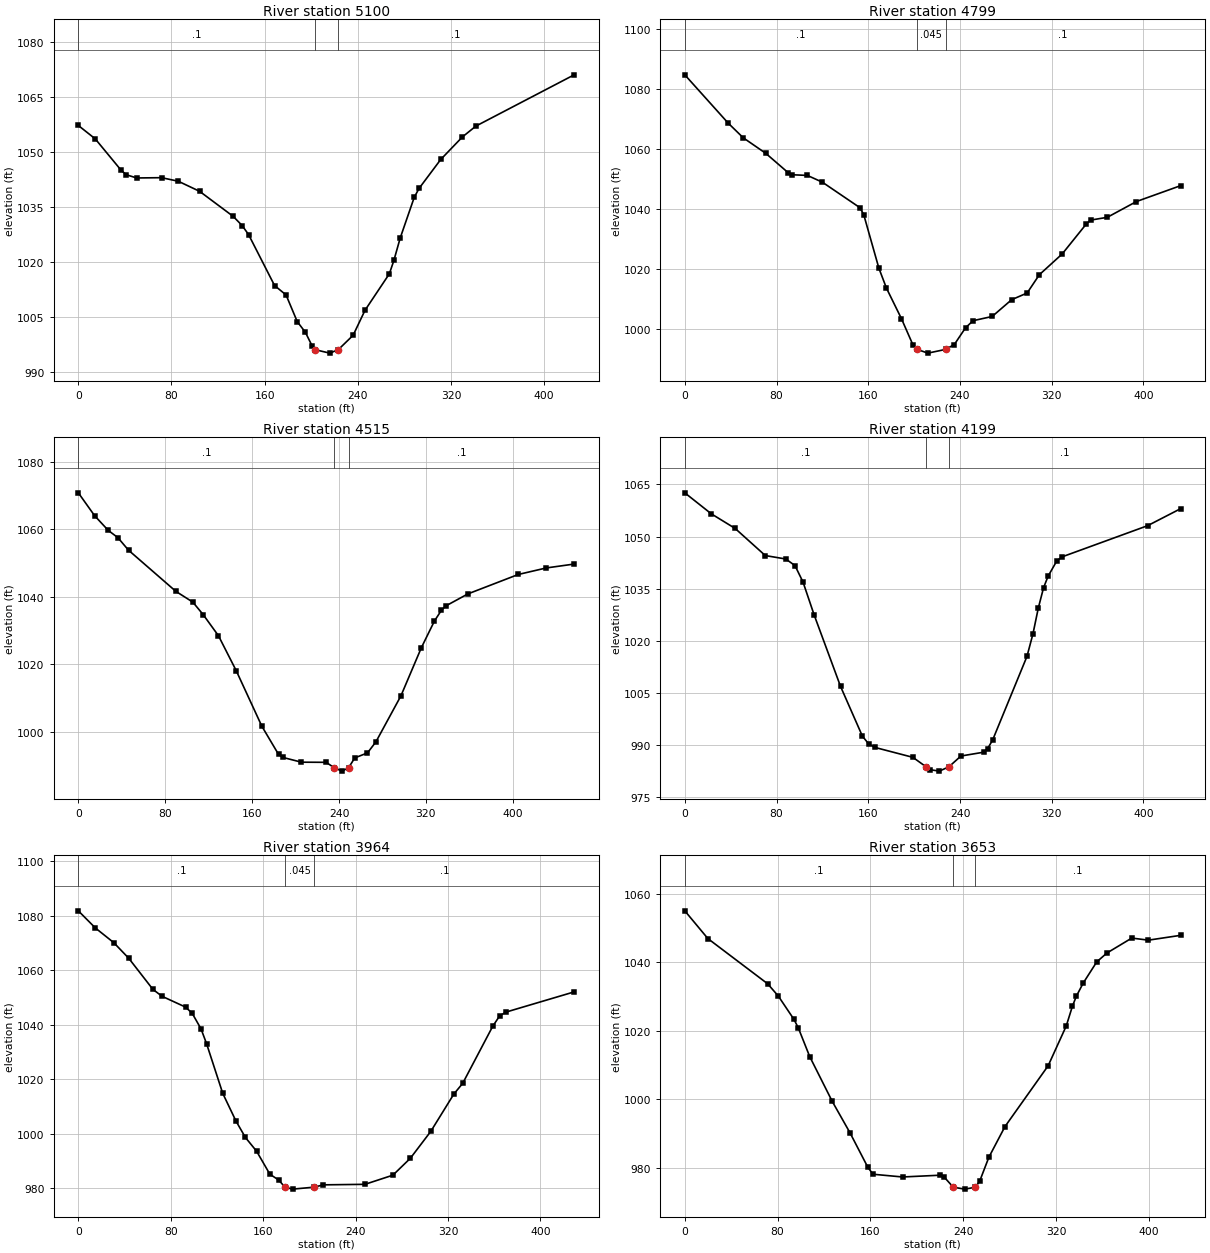
Type RM Length L Ch R = 1 ,5100    ,307.7,301.5,288.3
XS GIS Cut Line= 6
1647071.98853233492617.741440177  1647012.416473492682.391245261
1646959.90476701  492736.41574351646885.00793517 492802.67643775
1646828.83449109492852.3712202611646763.72110426 492910.82517159
#Sta/Elev= 30
       0  1057.3    14.5 1053.65    36.8 1045.04    41.2 1043.83    50.1 1042.95
    71.5 1043.03    85.8 1042.06   104.1 1039.31   133.1 1032.42   140.7 1029.93
   146.2 1027.47   168.5 1013.55   178.4 1010.96     188 1003.67     195 1000.75
   200.9  996.94   203.3996.0009   215.9  995.06  223.23996.0005     236  999.95
   246.2 1006.78   267.1 1016.75     271 1020.42   276.4 1026.52   288.5 1037.68
   292.6 1040.09   311.2    1048   329.8 1054.16   341.4 1057.13   425.8 1071.15
#Mann= 3 ,-1,0
       0      .1       0   203.3    .045       0  223.23      .1       0
Bank Sta=203.3,223.23
XS Rating Curve= 0 ,0
Exp/Cntr(USF)=0,0
Exp/Cntr=0.3,0.1

Type RM Length L Ch R = 1 ,4799    ,280,284,286.6
XS GIS Cut Line= 6
1646728.98987451492360.8515340091646725.10471167492448.265073091
1646721.77466585492523.1911043381646714.41214776492622.962558344
1646694.86100575 492697.164181591646654.31581126492781.104958594
#Sta/Elev= 30
       0 1084.86    37.9 1068.72      51 1063.84    70.7 1058.64    90.4 1052.12
    93.7 1051.51   106.9 1051.29     120 1049.03   152.8 1040.51   156.1 1038.17
   169.3 1020.32   175.9 1013.67     189 1003.46   198.9  994.82  202.79993.2134
     212  991.98  227.44993.2134   235.1  994.85   244.9 1000.45   251.5 1002.81
   268.1 1004.21   285.1 1009.81   298.6 1012.04   309.3 1018.16   329.2 1025.08
   350.3 1035.12     354 1036.38   368.5  1037.3     394 1042.58   432.5 1047.87
#Mann= 3 ,-1,0
       0      .1       0  202.79    .045       0  227.44      .1       0
Bank Sta=202.79,227.44
XS Rating Curve= 0 ,0
Exp/Cntr(USF)=0,0
Exp/Cntr=0.3,0.1

Type RM Length L Ch R = 1 ,4515    ,313,315.8,314.7
XS GIS Cut Line= 6
1646572.16636926  492340.08582751646520.13957043492424.006919503
1646468.39656368492497.2259331791646411.45409226492586.168340594
1646389.63622251492657.9306642561646363.21796826492741.374066919
#Sta/Elev= 30
       0 1070.86      15 1064.08    27.5 1059.74    36.4 1057.58    46.2 1053.86
    89.8 1041.66   105.4 1038.47   114.9 1034.78     129 1028.51   145.5 1018.06
     169 1001.66   184.3  993.36   188.3  992.44   205.4  991.03   228.2  990.99
  235.67989.3634   242.8  988.38  248.78989.3627   254.5   992.3   266.2  993.78
     274  997.07     297 1010.69   315.8 1024.95   327.8 1032.83   334.2 1036.02
   338.1  1037.3   358.7 1040.91     405 1046.66   430.9  1048.6   456.5 1049.75
#Mann= 3 ,-1,0
       0      .1       0  235.67    .045       0  248.78      .1       0
Bank Sta=235.67,248.78
XS Rating Curve= 0 ,0
Exp/Cntr(USF)=0,0
Exp/Cntr=0.3,0.1

Type RM Length L Ch R = 1 ,4199    ,234.6,234.8,228.5
XS GIS Cut Line= 6
1646350.59561817492202.0923370871646297.08653884492277.937985927
 1646250.0167511492338.903743252  1646186.024425492415.787447751
1646136.63640042492472.2305763361646079.01676501492538.080510259
#Sta/Elev= 30
       0 1062.58    23.1 1056.54    43.9 1052.33    70.2 1044.52    88.1 1043.53
    96.1 1041.63   103.1  1036.9   112.8 1027.43   135.8 1006.87   154.9  992.52
   160.3  990.34   165.7   989.3   198.9  986.44  210.35983.7304   213.5   982.9
     222  982.47   230.4983.7327   240.8  986.82   260.5  987.91   264.1  988.97
   268.4  991.38   298.4 1015.49   303.6 1021.96   308.3 1029.43   312.9  1035.3
   316.9 1038.63   324.5 1043.03   329.2 1044.17   403.6 1053.12   432.4 1058.02
#Mann= 3 ,-1,0
       0      .1       0  210.35    .045       0   230.4      .1       0
Bank Sta=210.35,230.4
XS Rating Curve= 0 ,0
Exp/Cntr(USF)=0,0
Exp/Cntr=0.3,0.1

Type RM Length L Ch R = 1 ,3964    ,305.9,310.8,309.3
XS GIS Cut Line= 2
1646173.84616232492027.5906841171645961.50092392492400.564052999
#Sta/Elev= 30
       0 1081.78    14.7 1075.51    30.7  1070.1    43.6  1064.4    64.6 1052.95
    72.5 1050.43    92.9 1046.46    98.6 1044.17   106.2 1038.49     111 1033.07
     125 1014.85   136.4 1004.73   144.6  998.68   154.3  993.63   165.8  985.19
   173.5  983.04  178.82980.4505   185.5  979.72   204.4 980.452     212  981.29
   248.1  981.48   272.3  984.84   287.4  991.03   305.1  1000.9   325.1 1014.61
   332.7  1018.5   358.7 1039.43   364.8 1043.31   370.4 1044.67   429.2 1052.05
#Mann= 3 ,-1,0
       0      .1       0  178.82    .045       0   204.4      .1       0
Bank Sta=178.82,204.4
XS Rating Curve= 0 ,0
Exp/Cntr(USF)=0,0
Exp/Cntr=0.3,0.1

Type RM Length L Ch R = 1 ,3653    ,309.7,310.2,308.6
XS GIS Cut Line= 4
1645975.24609992491945.084215992 1645909.6683538492009.963679396
1645907.15677704492014.7745486371645660.34754021492233.456667572
#Sta/Elev= 30
       0 1055.09    19.9 1046.98    71.4 1033.78    80.6 1030.19    94.1 1023.37
    97.8 1020.92   107.7 1012.49   127.1  999.41   142.3   990.3   157.8  980.15
   162.2  978.13   187.7  977.33   220.3  977.85   223.6   977.3   231.4  974.35
   241.3  973.78   250.5  974.33   254.2  976.11   262.1  983.09     276  992.06
   313.2 1009.82   328.8 1021.44   334.1 1027.19   337.5 1030.13   343.4 1033.97
   355.1 1040.17   363.8 1042.75   385.3 1047.13   399.6 1046.52   427.4 1047.93
#Mann= 3 ,-1,0
       0      .1       0   231.4    .045       0   250.5      .1       0
Bank Sta=231.4,250.5
XS Rating Curve= 0 ,0
Exp/Cntr(USF)=0,0
Exp/Cntr=0.3,0.1

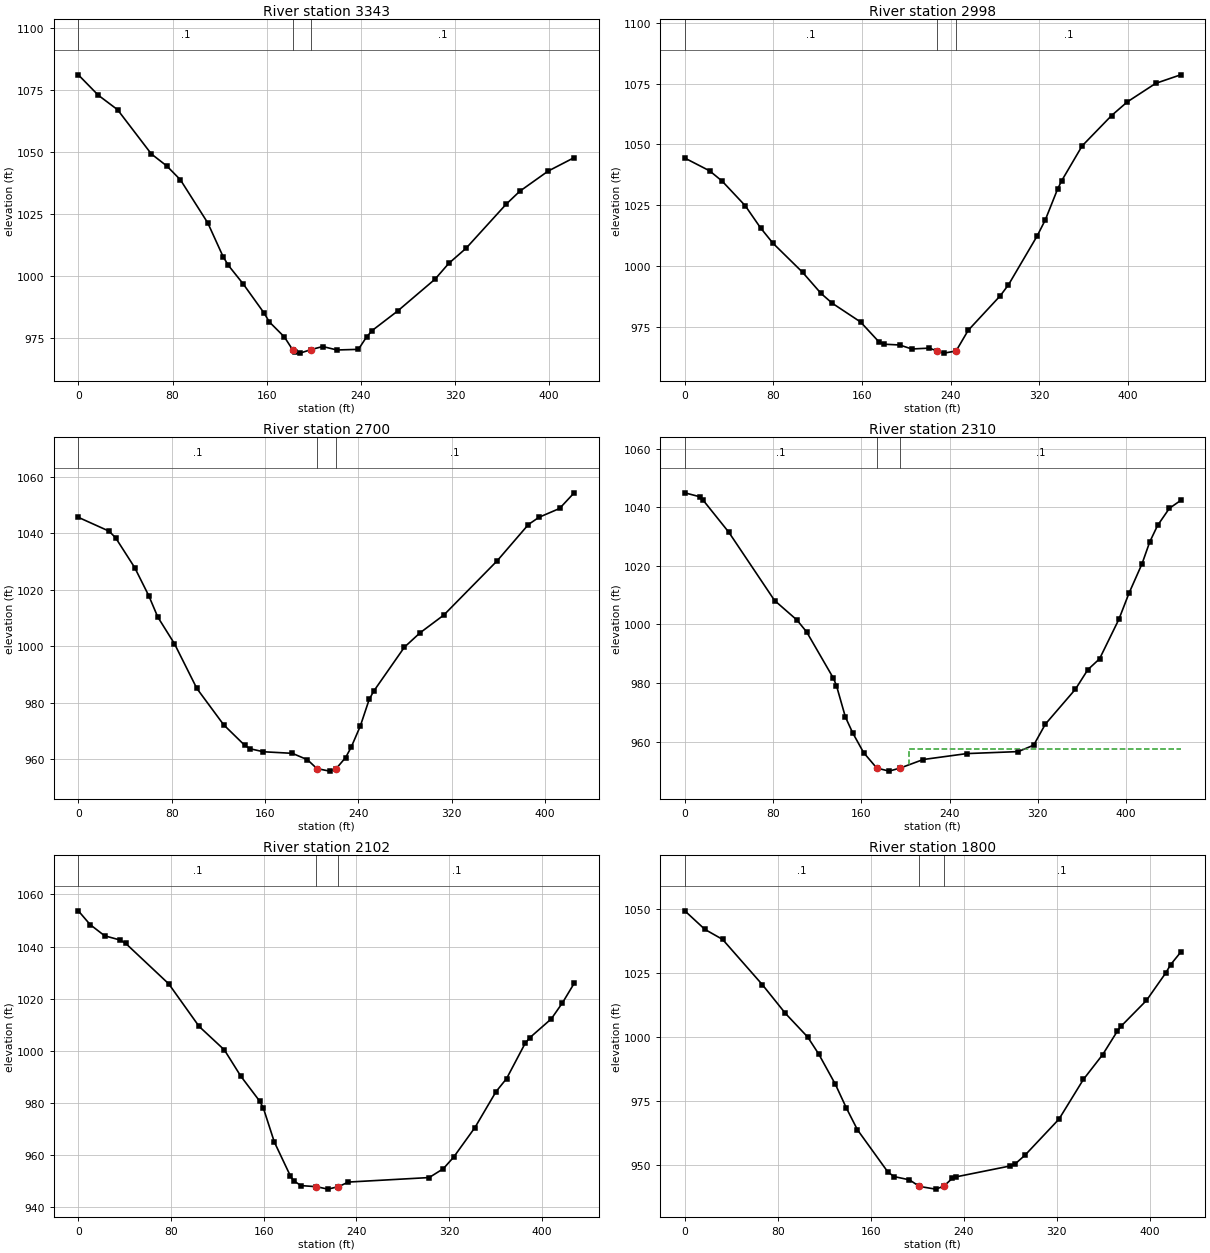
Type RM Length L Ch R = 1 ,3343    ,344.8,344.4,340.6
XS GIS Cut Line= 2
1645790.22645705491695.8901277261645512.99821201492012.962466002
#Sta/Elev= 30
       0 1081.22      17 1072.98    33.3 1067.17      62 1049.33    75.2 1044.45
    86.7  1038.9     110 1021.48     123 1007.89   127.4 1004.43     140  996.94
   157.9   985.1   162.2  981.62   175.1  975.49  181.97970.4248   184.4  969.28
   188.4  969.01  197.73970.4475   207.6  971.67   219.7  970.28   237.9  970.53
   244.8  975.49   249.6  978.12   271.2  985.97     303  998.82   314.7  1005.2
   329.4  1011.3   363.4 1029.04     375 1034.28   399.1 1042.41   421.2 1047.83
#Mann= 3 ,-1,0
       0      .1       0  181.97    .045       0  197.73      .1       0
Bank Sta=181.97,197.73
XS Rating Curve= 0 ,0
Exp/Cntr(USF)=0,0
Exp/Cntr=0.3,0.1

Type RM Length L Ch R = 1 ,2998    ,293.6,298.5,303.9
XS GIS Cut Line= 6
1645431.93013267491556.2786680911645399.43479083491653.682344675
1645383.56572808491734.4774586711645340.41489576491824.803065419
1645306.06752351491891.4659898431645265.99575326491969.237159759
#Sta/Elev= 30
       0  1044.4    22.4 1039.15    33.8 1034.88    54.6 1024.78    68.4 1015.68
    79.5 1009.42   106.3  997.43     123  988.72   133.1   984.7   158.7  976.98
   175.5  968.69   179.9  967.85     194  967.53   204.9  965.88   220.9  966.24
  227.56965.0612     234  964.18   244.9  965.06   255.8  973.54   284.8  987.78
   292.2  992.28   318.1 1012.37   325.5 1019.03   336.5 1031.61   340.2 1035.06
   358.7 1049.41   385.2 1061.86   399.5 1067.51   425.1 1075.12   447.6 1078.63
#Mann= 3 ,-1,0
       0      .1       0  227.56    .045       0   244.9      .1       0
Bank Sta=227.56,244.9
XS Rating Curve= 0 ,0
Exp/Cntr(USF)=0,0
Exp/Cntr=0.3,0.1

Type RM Length L Ch R = 1 ,2700    ,392.8,390.5,385.6
XS GIS Cut Line= 6
1645356.81479734491452.8615520891645280.84414876491496.274851084
1645215.72649685491533.486390844 1645128.9025235491583.100464836
1645063.78454351491620.3113484231644988.52353917491664.966442838
#Sta/Elev= 30
       0  1045.6    26.3 1040.72    31.9  1038.4    48.3 1027.84    60.4 1017.87
    68.1 1010.35    82.4 1000.91   101.6   985.1   124.6  972.25   142.5  965.05
   147.3  963.78   158.6  962.73   183.4  962.17   196.4  959.91  204.41956.8009
   215.3  955.88  221.08956.8009   229.1  960.67   233.9  964.35   241.7  971.81
   249.3  981.21   253.1  984.09   279.5   999.7   292.9 1004.77   313.3 1011.06
   359.1 1030.27   385.8 1043.06   394.8  1045.6   412.5 1048.73     425 1054.26
#Mann= 3 ,-1,0
       0      .1       0  204.41    .045       0  221.08      .1       0
Bank Sta=204.41,221.08
XS Rating Curve= 0 ,0
Exp/Cntr(USF)=0,0
Exp/Cntr=0.3,0.1

Type RM Length L Ch R = 1 ,2310    ,206.8,207.3,207.7
XS GIS Cut Line= 3
1645097.54749823491102.5733842121644912.13813519491309.720377737
1644851.54421969491470.131399962
#Sta/Elev= 30
       0 1044.97    13.5 1043.64    16.3 1042.61    39.9 1031.51    81.4 1008.19
   101.6 1001.55   110.4   997.5   134.8   981.6   137.5  979.11   145.6  968.39
   152.2  962.99   162.1  956.25  173.98950.9806   185.2  949.92  195.33  950.98
   216.2  953.89   255.7  955.91   302.3  956.59   316.3  958.79   326.9  965.98
   354.1  977.88   365.4  984.58     376  988.27   393.5 1001.75   402.7 1010.69
   414.5 1020.73   421.5  1028.2   428.6 1033.82   439.3 1039.68   449.5 1042.35
#Mann= 3 ,-1,0
       0      .1       0  173.98    .045       0  195.33      .1       0
#XS Ineff= 2 , 0
                          202.89           957.6
Permanent Ineff=
       F       F
Bank Sta=173.98,195.33
XS Rating Curve= 0 ,0
Exp/Cntr(USF)=0,0
Exp/Cntr=0.3,0.1

Type RM Length L Ch R = 1 ,2102    ,301,302.2,299.6
XS GIS Cut Line= 6
1644966.47469875490963.625325844 1644902.4446431491024.787605092
1644846.85715584491076.6592205021644776.25821568491147.720430091
1644725.80752917491203.2157259291644674.95822142491275.104361668
#Sta/Elev= 30
       0 1053.73    10.2 1048.44    22.7 1044.15    35.8 1042.56    40.8 1041.26
      78 1025.71   104.2 1009.38     126 1000.36   140.2  990.28   156.5  980.69
   159.6  978.11   169.1  965.03   182.9  952.07   185.7  950.17   192.2   948.3
   205.4  947.89   215.3  946.95  224.41947.8907     233  949.66   302.7  951.39
   314.9  954.78   323.8  959.21   342.2  970.59   360.4  984.36   369.5  989.37
   385.5 1002.87   389.5 1005.04   408.1 1012.29   417.7 1018.43   427.8  1025.9
#Mann= 3 ,-1,0
       0      .1       0   205.4    .045       0  224.41      .1       0
Bank Sta=205.4,224.41
XS Rating Curve= 0 ,0
Exp/Cntr(USF)=0,0
Exp/Cntr=0.3,0.1

Type RM Length L Ch R = 1 ,1800    ,331.9,334.6,334.9
XS GIS Cut Line= 6
1644659.99598101490822.1128135921644615.25886576490898.384314582
1644575.27010059490962.3750002531644513.38210101491040.923727676
1644466.96618333491099.8353552521644412.81471685491168.565532759
#Sta/Elev= 30
       0 1049.37    17.3 1042.11    32.5  1038.2    66.8 1020.45    86.6 1009.25
   105.7 1000.04   115.2  993.38   129.5  981.57     139  972.26   148.5  963.78
   174.5  947.39   179.8  945.53   193.2  944.24  201.67941.6777   215.6  940.61
  222.54941.6771   229.9  944.77   232.9  945.37     280  949.68   284.2  950.51
   292.5  953.84   321.8  967.97   342.8  983.49   359.4   993.2   371.9 1002.29
   375.4 1004.37     397 1014.34   413.7 1025.15   417.8 1028.34   426.4 1033.17
#Mann= 3 ,-1,0
       0      .1       0  201.67    .045       0  222.54      .1       0
Bank Sta=201.67,222.54
XS Rating Curve= 0 ,0
Exp/Cntr(USF)=0,0
Exp/Cntr=0.3,0.1

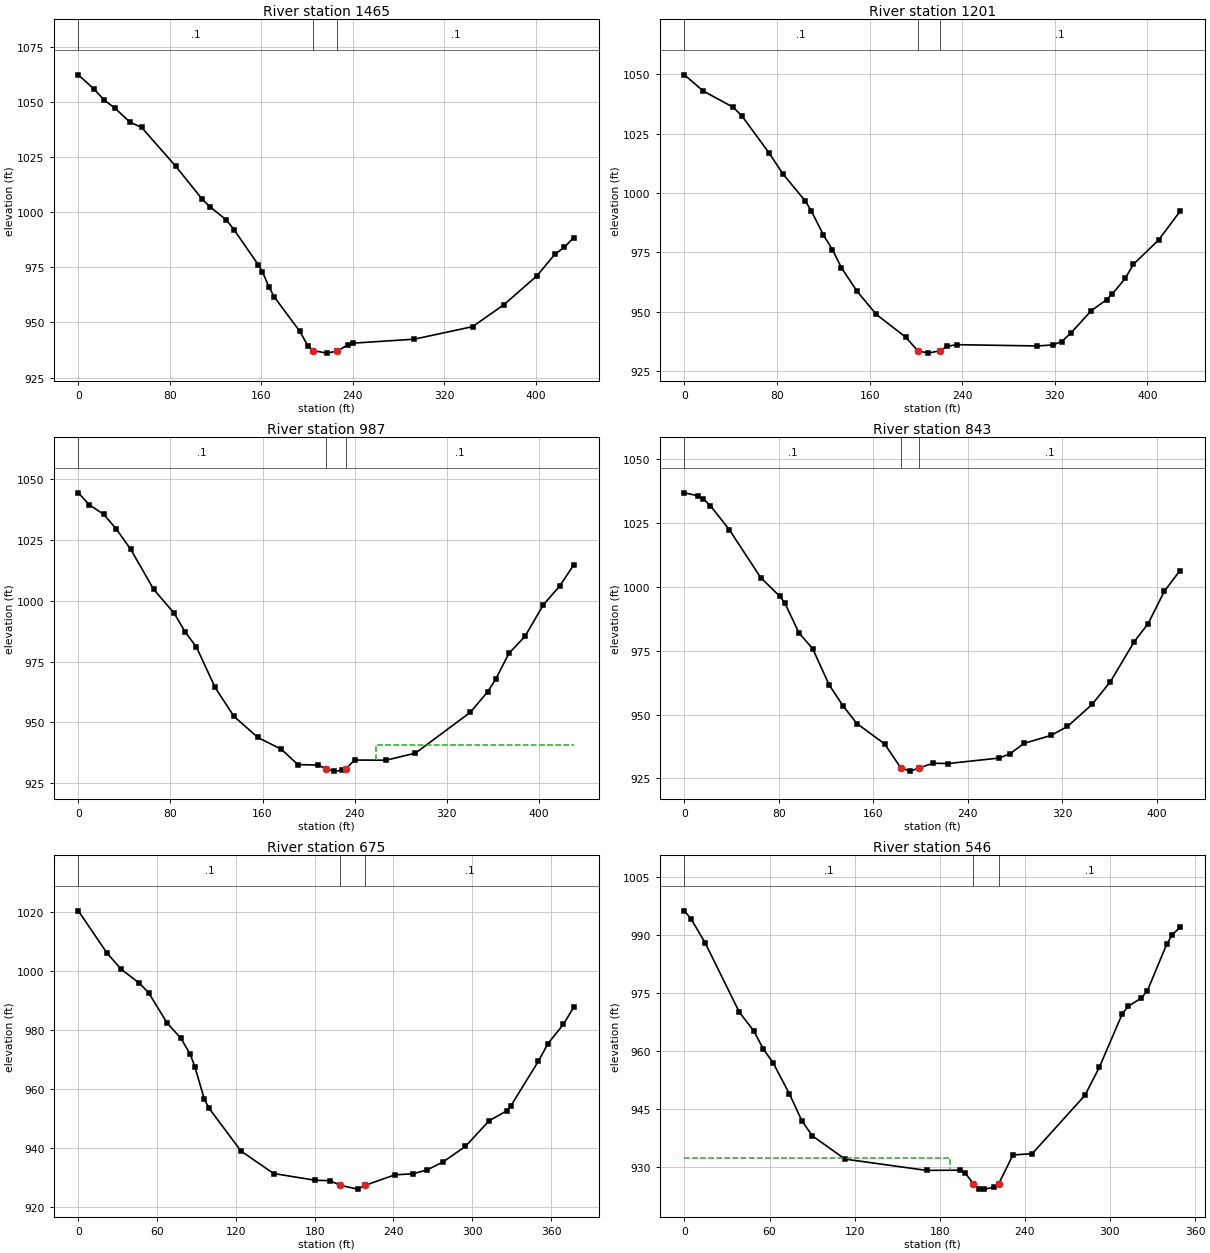
Type RM Length L Ch R = 1 ,1465    ,262.4,264.5,265.5
XS GIS Cut Line= 6
1644500.42471177490591.9114362661644438.55410059490653.784672103
1644385.52205444 490706.818686761644314.21347001490777.118086851
1644258.87007676490831.8617437691644190.84002909490895.117850846
#Sta/Elev= 30
       0 1062.29    13.7 1055.84    22.4 1050.96    32.2 1047.08    45.1 1040.86
    55.4 1038.41    85.1 1020.91   108.3 1005.92   115.2 1002.43   129.6  996.43
   136.1  992.12   157.5  976.08   161.1   972.9   166.7  966.17   171.3  961.62
   193.8   945.9     201  939.18   205.7   937.2   217.2  936.07   226.6     937
   226.6  937.02   235.8  939.84   240.5   940.6   293.8  942.39   344.9  948.09
   372.2  958.02   401.1   971.1   416.8  980.89   425.2  984.11   433.4   988.5
#Mann= 3 ,-1,0
       0      .1       0   205.7    .045       0   226.6      .1       0
Bank Sta=205.7,226.6
XS Rating Curve= 0 ,0
Exp/Cntr(USF)=0,0
Exp/Cntr=0.3,0.1

Type RM Length L Ch R = 1 ,1201    ,215.3,213.5,211.6
XS GIS Cut Line= 6
1644342.50317767490446.4367276731644268.70247225490493.729940176
1644205.61532809490534.498887509 1644123.6092585490591.758943588
 1644068.2944085490643.3247853371644009.72858076490711.265594333
#Sta/Elev= 30
       0 1049.76    16.3 1042.94    42.1 1036.11    49.6 1032.49    73.3 1016.76
      85 1008.07   104.5   996.6   109.7  992.39   120.1  982.31   127.9  976.11
   135.7   968.5   149.2  958.57   165.8  948.85   191.1  939.31  201.59933.5507
   210.6  932.54  220.92933.5499   227.1   935.4   235.1   936.1     305  935.56
   318.2  935.99     326  937.41   333.8  940.94   351.6  950.46   364.7  955.01
   369.7  957.46   380.9  964.05   387.9  969.92   409.9   980.3   428.1  992.22
#Mann= 3 ,-1,0
       0      .1       0  201.59    .045       0  220.92      .1       0
Bank Sta=201.59,220.92
XS Rating Curve= 0 ,0
Exp/Cntr(USF)=0,0
Exp/Cntr=0.3,0.1

Type RM Length L Ch R = 1 ,987     ,143.5,144.1,144.3
XS GIS Cut Line= 2
1644167.74729359490280.4278733431643858.70750682490579.847707895
#Sta/Elev= 30
       0 1044.39     9.7 1039.38      22 1035.59      33 1029.49    45.6 1021.09
    65.4 1004.73    83.3  994.85    92.7  987.23   102.6  980.93   118.8  964.35
   135.1   952.5   155.9  943.78   176.1  939.01   190.7  932.65     208  932.44
  214.83931.0201   221.7  929.95   229.4  930.21  232.57931.0181     240  934.51
   267.3  934.44   292.8  937.36   340.5  954.15   355.5  962.57   362.4  967.71
     374  978.39   387.9  985.36   403.9  998.36   418.2 1006.16   430.3  1014.8
#Mann= 3 ,-1,0
       0      .1       0  214.83    .045       0  232.57      .1       0
#XS Ineff= 2 , 0
                          258.12          940.53
Permanent Ineff=
       F       F
Bank Sta=214.83,232.57
XS Rating Curve= 0 ,0
Exp/Cntr(USF)=0,0
Exp/Cntr=0.3,0.1

Type RM Length L Ch R = 1 ,843     ,163,167.8,170.3
XS GIS Cut Line= 2
1644076.66189346490177.3476606721643775.97840292 490470.37042534
#Sta/Elev= 30
       0 1036.84    11.3  1035.7    15.9 1034.57    21.9 1031.85      38 1022.44
    64.6 1003.64    80.9  996.28      85  993.74    97.1  981.93   108.7  975.76
   122.6  961.63   134.2  953.52   146.1  946.48   169.6  938.49  183.42 929.056
   191.4  927.83   198.5929.0555   210.8  930.92   223.5  930.81   266.5  932.95
   275.8   934.6   287.6  938.69   310.5   941.8   324.5  945.32   345.4  953.96
   360.9  962.86   381.1  978.53   392.9  985.64   406.7  998.34   419.8 1006.36
#Mann= 3 ,-1,0
       0      .1       0  183.42    .045       0   198.5      .1       0
Bank Sta=183.42,198.5
XS Rating Curve= 0 ,0
Exp/Cntr(USF)=0,0
Exp/Cntr=0.3,0.1

Type RM Length L Ch R = 1 ,675     ,127.4,129.6,129.6
XS GIS Cut Line= 4
1644009.16483053490124.8110185931643886.82780418490172.433409937
1643759.87644476 490224.671165851643671.68014672490288.320570726
#Sta/Elev= 30
       0 1020.27    21.8 1006.03    32.4 1000.63    46.4  995.84    53.5  992.61
    67.6  982.37    78.2  977.13    85.2   971.8    88.7  967.65    95.8   956.8
    99.3  953.69   123.9  939.06   148.7  931.48   180.6  929.18   191.3  929.07
   199.6  927.48   212.6   926.2  218.39927.4761     241  931.02   255.1  931.41
   265.8  932.75   277.7  935.37   294.7  940.62   312.9  949.33   326.1  952.63
   329.4  954.37   350.4  969.49   357.6  975.39   369.3  981.85   377.3  987.76
#Mann= 3 ,-1,0
       0      .1       0   199.6    .045       0  218.39      .1       0
Bank Sta=199.6,218.39
XS Rating Curve= 0 ,0
Exp/Cntr(USF)=0,0
Exp/Cntr=0.3,0.1

Type RM Length L Ch R = 1 ,546     ,50.4,51.9,52.1
XS GIS Cut Line= 2
1643947.54910409490049.7280244991643609.04650024490135.869228349
#Sta/Elev= 30
       0  996.24     4.8  994.08    14.6  987.98    38.7  970.06    48.8  965.27
    55.6  960.56    62.4  957.05      74  948.96    82.7  942.06    90.1  938.13
   113.2   932.1   170.7  929.18   194.4  929.24   197.8  928.58  203.62925.7665
   207.9  924.47   211.3  924.34   218.1   924.8  221.66925.7678   231.6  933.17
   245.2   933.5   282.4  948.59   292.6   955.9   308.7  969.65   312.9  971.57
   322.2  973.73   326.4  975.62     340  987.62   343.8  990.01   349.3  991.97
#Mann= 3 ,-1,0
       0      .1       0  203.62    .045       0  221.66      .1       0
#XS Ineff= 2 , 0
          187.26   932.4
Permanent Ineff=
       F       F
Bank Sta=203.62,221.66
XS Rating Curve= 0 ,0
Exp/Cntr(USF)=0,0
Exp/Cntr=0.3,0.1