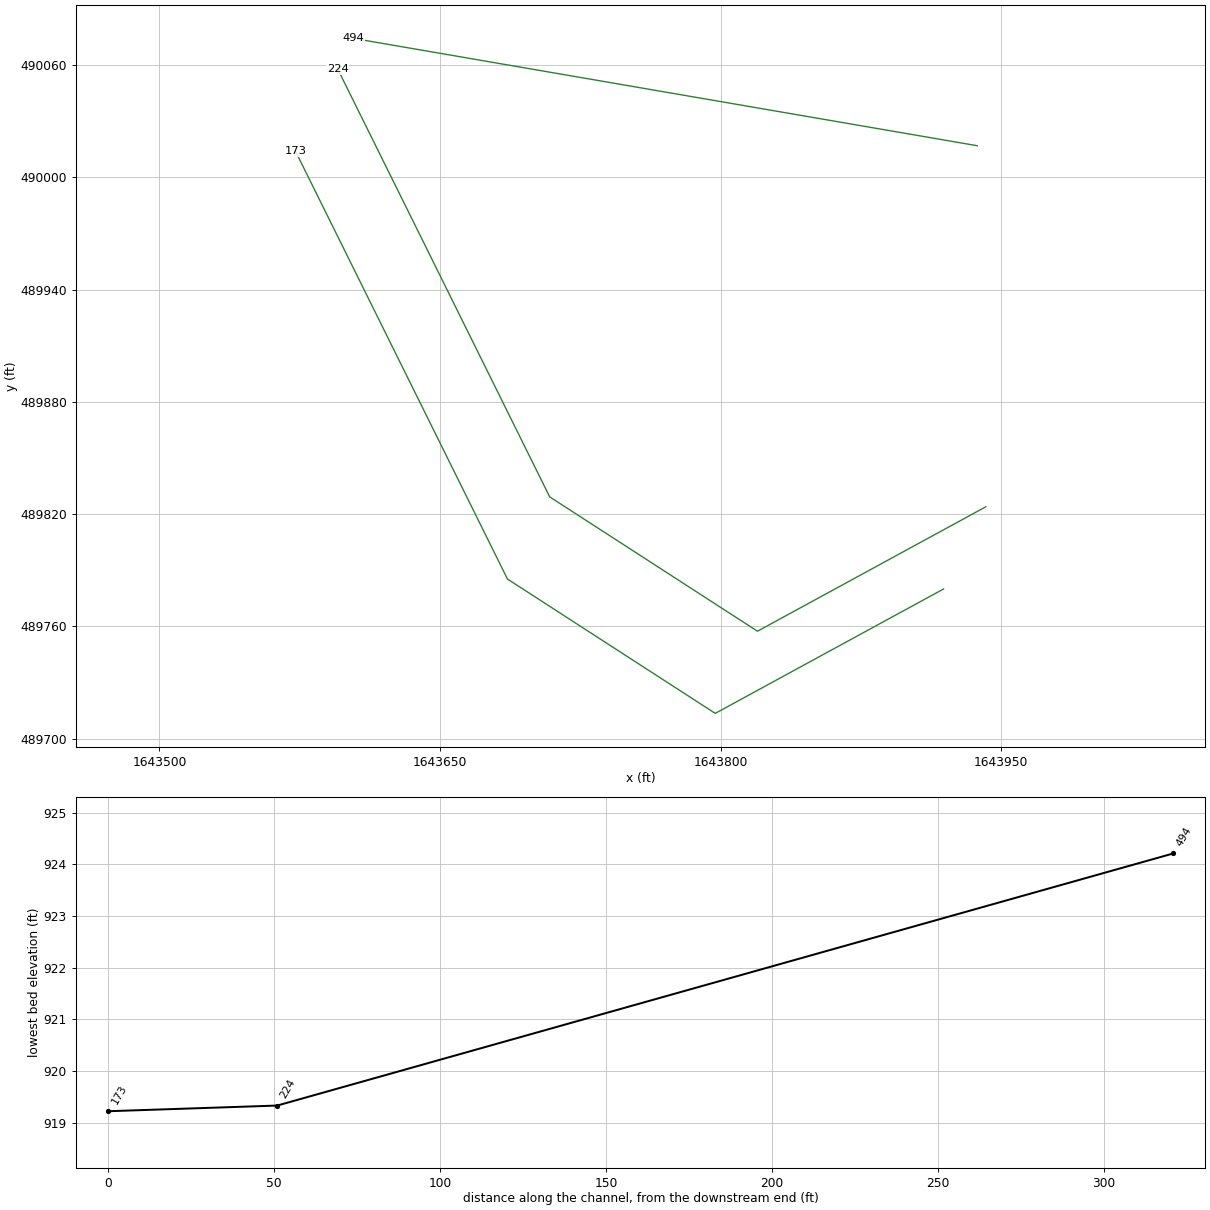
HEC-RAS study FrenchRn.prj: FrenchRn

--- FrenchRn.g01 (geometry) --- (continued)

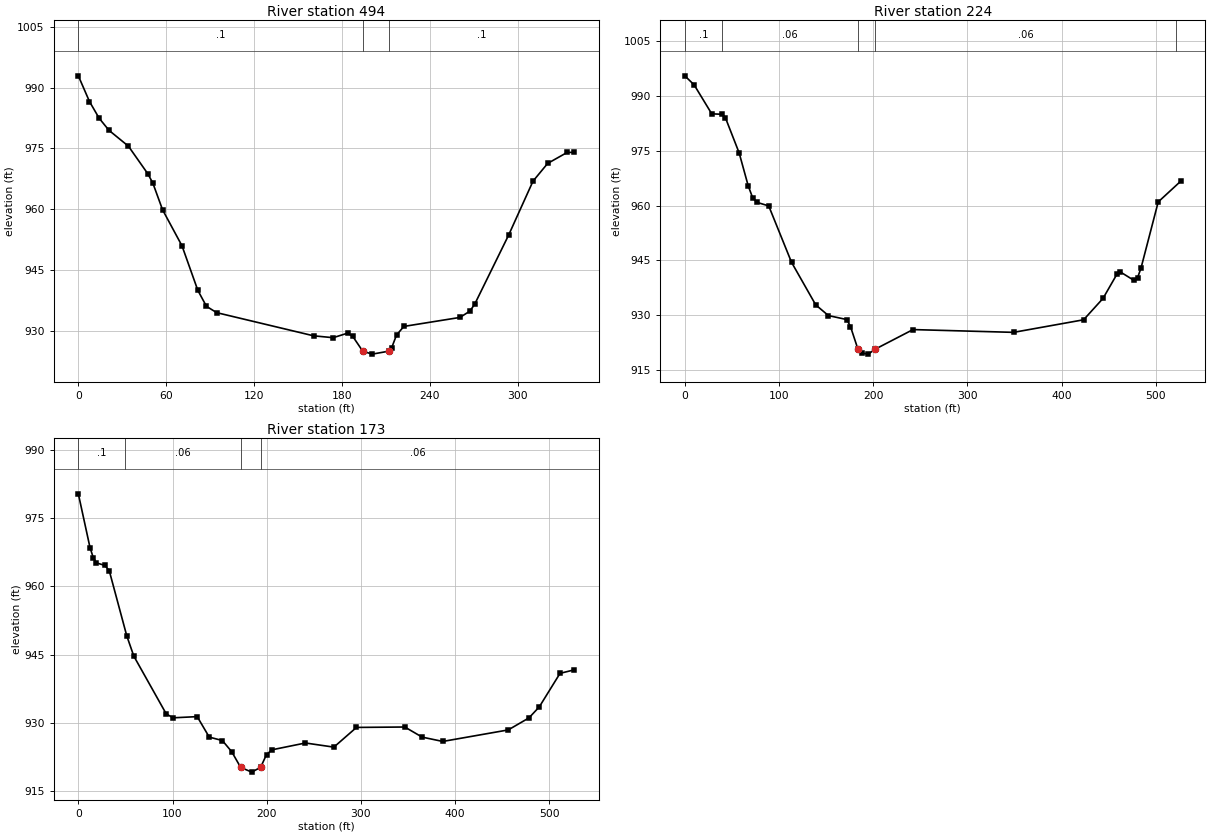
Type RM Length L Ch R = 1 ,494     ,275.5,269.9,268.7
XS GIS Cut Line= 2
 1643937.2341798490016.9348884951643603.51952963490074.348370319
#Sta/Elev= 30
       0  992.93     7.6  986.59    14.2  982.47    20.9  979.48    34.2  975.56
    47.5  968.72    50.9  966.43    57.5  959.87    70.8  950.95    81.6  939.96
    87.5  936.01    94.5  934.45   160.7  928.73     174  928.27     184   929.4
   187.4  928.59  194.24924.9305   200.7  924.21  211.91924.9313     214   925.8
   217.3  928.93   222.3  931.05   260.6  933.27   267.3  934.81   270.6  936.48
   293.9  953.64   310.5  966.92   320.5   971.3   333.8  974.01   338.6  974.04
#Mann= 3 ,-1,0
       0      .1       0  194.24    .045       0  211.91      .1       0
Bank Sta=194.24,211.91
XS Rating Curve= 0 ,0
Exp/Cntr(USF)=0,0
Exp/Cntr=0.3,0.1

Type RM Length L Ch R = 1 ,224     ,51.8,51,51
XS GIS Cut Line= 4
1643941.73110316489823.9064826031643819.69277753489757.406818411
1643708.61225236489829.226123477 1643595.3393869490057.831695612
#Sta/Elev= 30
       0  995.51     9.9  993.04    28.6  985.11    39.8  984.98    43.1  984.05
    57.7  974.41    67.3  965.42    72.2  962.02    76.7  960.87    89.1   959.9
   113.3  944.47     139  932.81   152.5  929.88     172  928.79   175.9  926.88
  183.81920.6821   187.6  919.63   194.8  919.33  202.13920.6846   242.3  926.05
   349.1  925.29   423.4  928.73     444  934.58   459.2   941.4   462.3  941.84
     477   939.5   480.7  940.27   484.3  942.85   502.6  960.99   526.4  966.64
#Mann= 5 ,-1,0
       0      .1       0      40     .06       0  183.81    .045       0
  202.13     .06       0  521.26      .1       0
Bank Sta=183.81,202.13
XS Rating Curve= 0 ,0
Exp/Cntr(USF)=0,0
Exp/Cntr=0.3,0.1

Type RM Length L Ch R = 1 ,173     ,,,
XS GIS Cut Line= 4
1643919.15414913489779.986615499 1643797.1158235489713.486951307
1643686.03529833489785.3062563731643572.76243287490013.911828508
#Sta/Elev= 30
       0  980.35    12.4  968.54    15.9  966.31    19.2  965.18      28  964.64
    32.8  963.49    51.4  949.17    58.9   944.7    93.3  932.02   100.5  931.15
   126.2  931.41     139  926.91   152.9  926.16   162.8  923.72   172.3 920.272
   184.1  919.22  193.51920.2719   199.8  923.08   205.5  924.12   241.1  925.62
   271.3  924.71   295.3  929.04   346.6  929.13     365  926.91   386.9  925.96
   456.4  928.49   478.4  931.13   489.4  933.56   511.4  940.92   526.4  941.68
#Mann= 4 ,-1,0
       0      .1       0      50     .06       0   172.3    .045       0
  193.51     .06       0
Bank Sta=172.3,193.51
XS Rating Curve= 0 ,0
Exp/Cntr(USF)=0,0
Exp/Cntr=0.3,0.1
LCMann Table=0

Chan Stop Cuts=-1
Use User Specified Reach Order=0
Composite Channel Slope=5